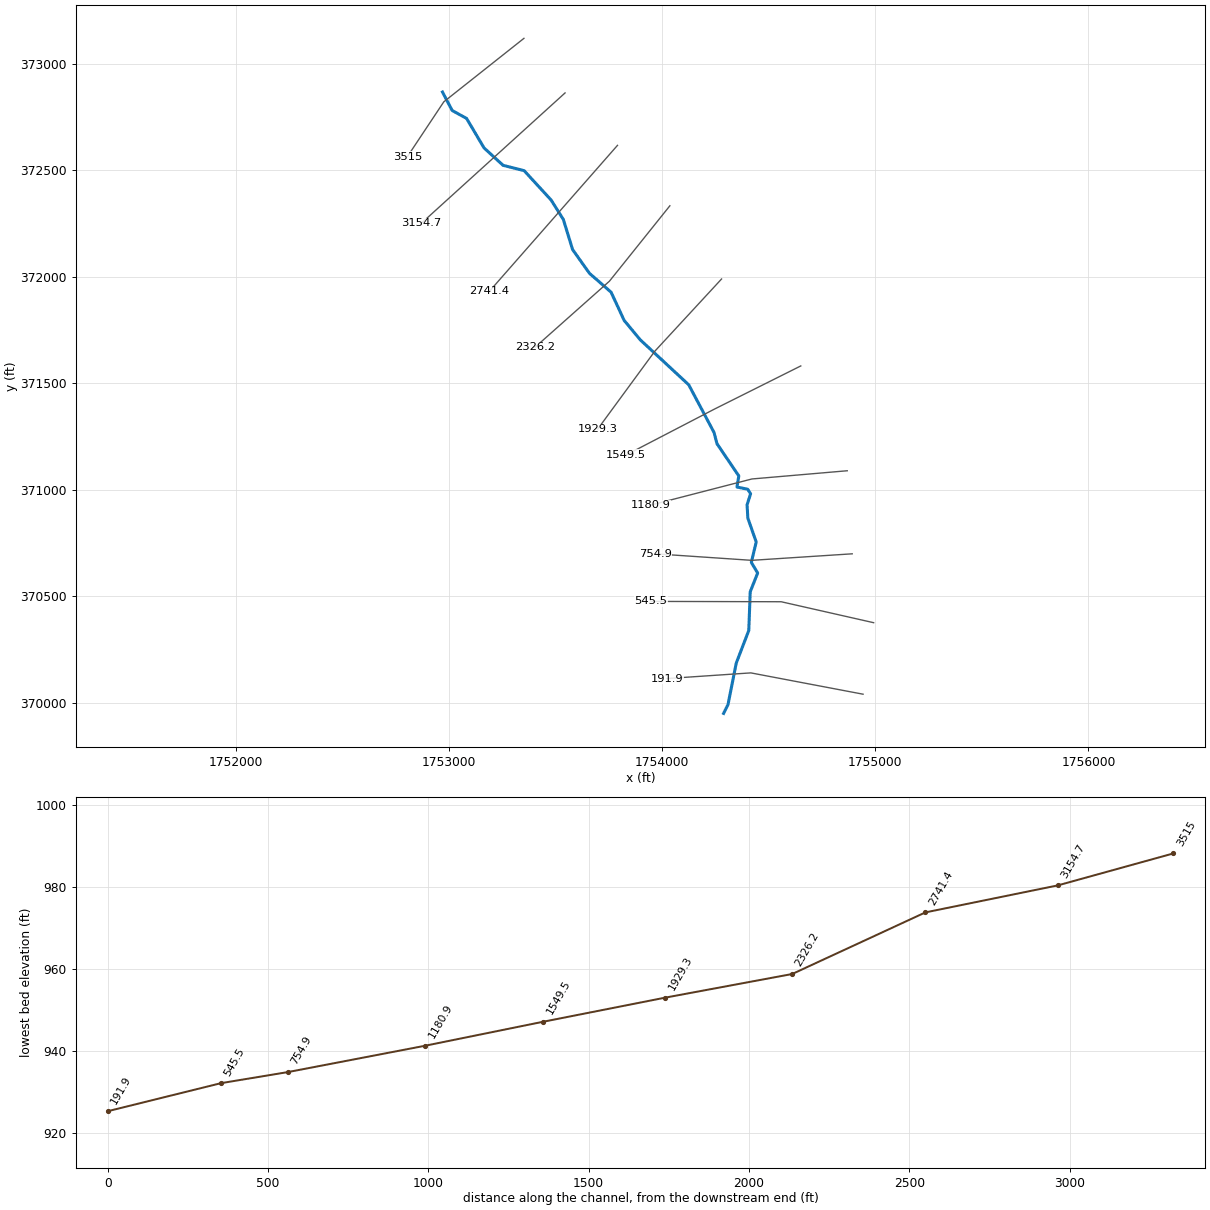
--- LrlRn2.prj (project) ---

Proj Title=LrlRn2
Current Plan=p01
Default Exp/Contr=0,0
English Units
Geom File=g01
Flow File=f01
Plan File=p01
BEGIN DESCRIPTION:
END DESCRIPTION:
DSS Export Rating Curves= 0
DSS Export Rating Curve Sorted= 0
DSS Export Volume Flow Curves= 0
DXF OffsetX= 0
DXF OffsetY= 0
DXF ScaleX= 0
DXF ScaleY= 0

--- LrlRn2.p01 (plan) ---

Plan Title=Floodplain
Program Version=4.00
Geom File=g01
Flow File=f01
K Sum by GR=0
Std Step Tol=0.01
Critical Tol=0.01
Num of Std Step Trials=20
Max Error Tol=0.3
Flow Tol Ratio=0.001
Split Flow NTrial=30
Split Flow Tol=0.02
Split Flow Ratio=0.02
Log Output Level=0
Friction Slope Method=1
Unsteady Friction Slope Method=2
Unsteady Bridges Friction Slope Method=1
Global Log Level=0
CheckData=False
Run HTab=0
Run UNet=0
Run PostProcess=0
UNET Theta=0
UNET Theta Warmup=0
UNET ZTol=0
UNET ZSATol=0
UNET MxIter=0
UNET MaxInSteps=0
UNET DtIC=0
UNET DtMin=0
UNET MaxCRTS=0
UNET WFStab=0
UNET SFStab=0
UNET WFX=0
UNET SFX=0
UNET DSS MLevel=0
UNET DZMax Abort=0
UNET Convert EG Bridges=0
UNET Use Existing IB Tables=0
UNET Froude Limit=0
UNET Froude Power=0
Write IC File=0
Echo Input=False
Echo Output=False
Write Detailed=0

--- LrlRn2.f01 (steady flow) ---

Flow Title=NFF Regression Equation
Program Version=4.00
Number of Profiles= 1
Profile Names=P100yr
River Rch & RM=LrlRn2,Main            ,3515
  730.54
River Rch & RM=LrlRn2,Main            ,3154.7
734.7888
River Rch & RM=LrlRn2,Main            ,1929.3
812.5216
Boundary for River Rch & Prof#=LrlRn2,Main            , 1
Up Type= 0
Dn Type= 3
Dn Slope=0.010778
DSS Import GetInterval= 0
DSS Import GetPeak= 0
DSS Import FillOption= 0

--- LrlRn2.g01 (geometry) ---

Geom Title=USGS 3m DEM
Program Version=4.00

River Reach=LrlRn2          ,Main
Reach XY= 30
     1752968.751      372867.482     1753014.324      372780.676
     1753081.598      372743.784     1753164.063      372604.895
     1753253.149      372523.583     1753352.067       372498.42
      1753478.75      372360.456     1753536.018      372269.348
     1753579.403      372127.914     1753659.231      372015.982
     1753759.883      371928.345      1753821.49      371795.587
     1753896.979      371704.479     1754124.315       371493.63
     1754243.189      371269.764     1754257.072      371216.835
      1754359.46      371065.856     1754350.783      371013.794
      1754401.11      371003.382     1754414.853      370982.313
     1754398.287      370930.429      1754401.78      370867.994
     1754441.128      370755.858     1754418.135      370659.818
     1754447.938      370610.168     1754412.952      370522.046
     1754406.316      370340.463     1754347.312      370186.881
     1754308.704      369992.451     1754288.207      369951.458

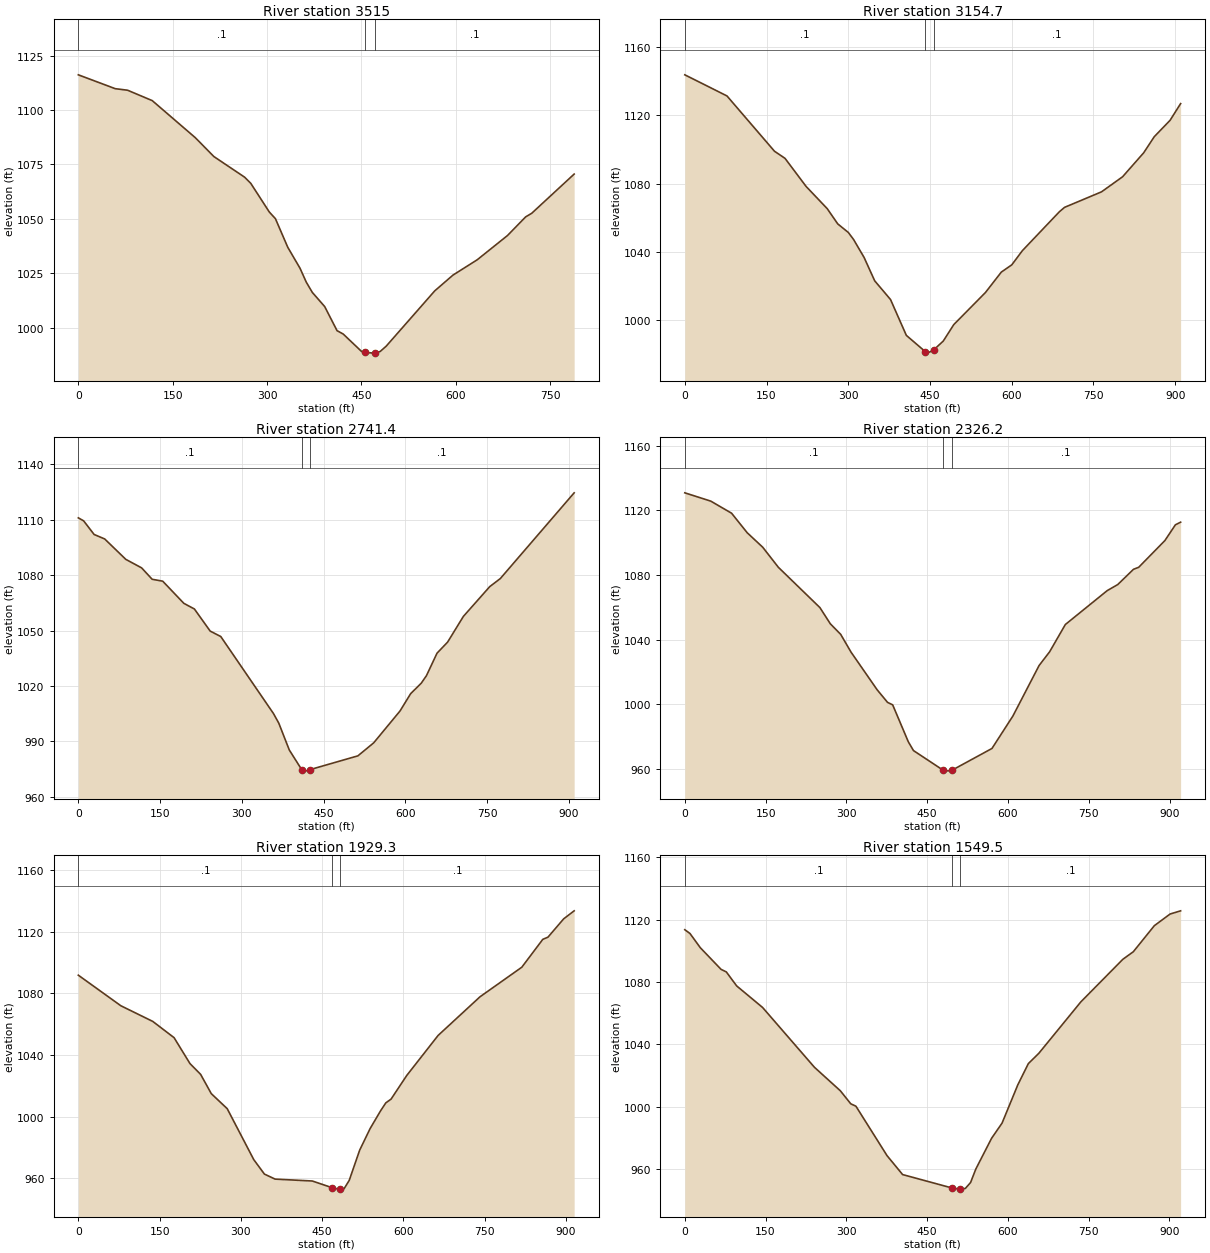
Type RM Length L Ch R = 1 ,3515    ,358.859,360.278,359.263
XS GIS Cut Line= 3
     1753351.146      373119.485     1752975.069      372821.636
     1752804.358      372564.799
#Sta/Elev= 30
       0 1116.16    58.7 1109.79    78.3 1109.08   117.5  1104.3     186 1087.25
   215.4  1078.6   264.3 1069.11   274.1 1066.27   303.5 1053.12   313.3 1050.02
   332.9 1036.88   352.5 1027.17   362.3 1020.85     372  1016.1   391.6 1009.62
   411.2  998.56     421     997   450.4  988.93   456.2  988.56   469.9  988.22
   471.2  988.32   479.7  988.95   489.4  991.43   566.5 1016.84   595.4 1024.07
   633.9 1031.11   682.1 1042.27     711 1050.85   720.7 1052.52   788.1 1070.53
#Mann= 3 , 0 , 0
       0      .1       0   456.2    .045       0   471.2      .1       0
Bank Sta=456.2,471.2
XS Rating Curve= 0 ,0
Exp/Cntr=0.3,0.1

Type RM Length L Ch R = 1 ,3154.7  ,410.683,413.279,415.875
XS GIS Cut Line= 3
        1753544.      372863.261     1753206.972      372557.585
     1752869.945       372251.91
#Sta/Elev= 30
       0 1143.81    77.4 1131.42   164.6 1098.95   183.9 1094.78   222.7 1078.26
   261.4 1065.24   280.7 1056.29   300.1 1051.26   309.8 1047.11   329.1 1036.57
   348.5 1022.88   377.6 1011.87   406.6  990.84   441.5  981.26   445.3  980.41
   456.5  982.21   474.4  987.51   493.7  997.17   551.8    1016   580.9 1027.98
   600.2 1032.27   619.6 1040.58   687.3 1063.36     697    1066   764.8  1075.1
   803.5 1083.96   842.2 1098.02   861.6 1107.47   890.6 1117.09     910 1126.92
#Mann= 3 , 0 , 0
       0      .1       0   441.5    .045       0   456.5      .1       0
Bank Sta=441.5,456.5
XS Rating Curve= 0 ,0
Exp/Cntr=0.3,0.1

Type RM Length L Ch R = 1 ,2741.4  ,418.128,415.181,412.234
XS GIS Cut Line= 3
     1753790.145      372617.295     1753490.032      372275.305
     1753189.918      371933.316
#Sta/Elev= 30
       0 1111.06     9.7 1109.44      29 1102.05    48.4 1099.62    87.1 1088.57
   116.2 1083.94   135.5 1077.77   154.9 1076.74   193.6 1064.74     213 1061.67
     242 1049.69   261.4 1046.75   358.2 1004.98   367.9   999.8   387.2  985.25
   410.2   974.5   416.3   973.8   425.2  974.61   513.1  982.08   542.1  989.13
   590.5 1006.43   609.9 1015.77   629.3 1021.44   638.9 1025.52   658.3 1037.71
   677.7  1043.7   706.7 1057.65   755.1 1073.79   774.5 1078.16     910 1124.62
#Mann= 3 , 0 , 0
       0      .1       0   410.2    .045       0   425.2      .1       0
Bank Sta=410.2,425.2
XS Rating Curve= 0 ,0
Exp/Cntr=0.3,0.1

Type RM Length L Ch R = 1 ,2326.2  ,393.112,396.955,401.688
XS GIS Cut Line= 3
     1754035.953      372333.683     1753752.368      371979.854
     1753403.236      371669.753
#Sta/Elev= 30
       0  1130.8    48.2 1125.67    86.8 1118.21   115.8 1106.14   144.7 1097.15
   173.7 1084.76   250.8 1059.85   270.1 1049.85   289.4  1043.3   308.7 1032.27
     357 1009.07   376.3 1001.27   385.9  999.72   414.9   976.9   424.5  971.46
   480.1  959.21   482.6  958.75   495.1  959.14   570.2  972.76   609.1  992.84
   657.7 1024.05   677.2 1032.51   706.4 1049.38   784.2 1070.36   803.7 1074.09
   832.9 1083.52   842.6 1084.77   891.2 1101.29   910.7 1111.03   920.4 1112.66
#Mann= 3 , 0 , 0
       0      .1       0   480.1    .045       0   495.1      .1       0
Bank Sta=480.1,495.1
XS Rating Curve= 0 ,0
Exp/Cntr=0.3,0.1

Type RM Length L Ch R = 1 ,1929.3  ,389.371,379.833,369.404
XS GIS Cut Line= 3
     1754278.459      371990.067     1753965.384      371651.229
     1753696.974      371285.216
#Sta/Elev= 30
       0  1091.8    78.5 1071.96   137.4  1061.8   176.7 1051.26   206.1 1034.43
   225.8 1027.41   245.4 1014.93   274.8 1005.18   323.9  972.06   343.5  962.72
   363.2  959.46   431.9  958.23   468.9  953.83   480.6  952.96   483.9  953.01
   490.3  953.11     500  958.62   519.3  978.24   538.6  992.27   557.9 1003.78
   567.6 1008.96   577.2 1011.35   606.2 1026.72   664.1  1052.7   741.4 1077.78
   818.6 1096.98   857.3 1115.05   866.9 1116.49   895.9 1128.38   915.2 1133.57
#Mann= 3 , 0 , 0
       0      .1       0   468.9    .045       0   483.9      .1       0
Bank Sta=468.9,483.9
XS Rating Curve= 0 ,0
Exp/Cntr=0.3,0.1

Type RM Length L Ch R = 1 ,1549.5  ,373.884,368.556,362.963
XS GIS Cut Line= 3
     1754650.337      371582.087     1754245.441      371379.638
     1753830.029      371163.874
#Sta/Elev= 30
       0  1113.5     9.6 1111.09    28.9 1101.92    67.4 1088.06    77.1 1086.43
    96.3 1077.46   144.5 1063.61   240.8 1025.24   288.9 1010.17   308.2 1001.83
   317.8 1000.28   375.6  968.56   404.5  956.42     496  947.83     511  947.09
   511.2  947.08     521  947.51   530.7  951.31   540.5     960   569.7  979.67
   589.2  989.44   618.5 1014.03     638  1027.6   657.5 1034.22   735.5  1067.2
   813.5 1094.52     833 1099.39     872  1116.1   901.3 1123.58   920.8 1125.62
#Mann= 3 , 0 , 0
       0      .1       0     496    .045       0     511      .1       0
Bank Sta=496,511
XS Rating Curve= 0 ,0
Exp/Cntr=0.3,0.1

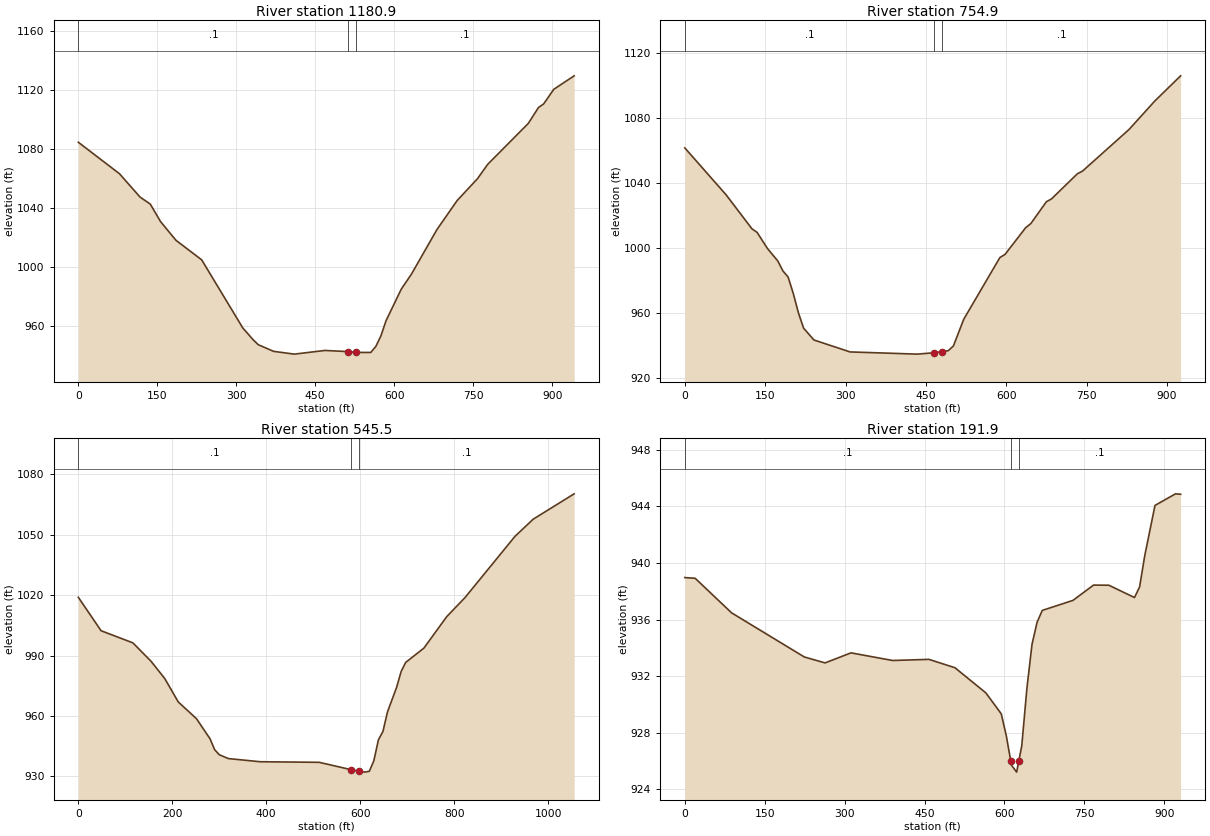
Type RM Length L Ch R = 1 ,1180.9  ,426.474,426.029,418.66
XS GIS Cut Line= 3
     1754868.445      371090.126      1754420.95       371051.56
     1753944.001      370928.353
#Sta/Elev= 30
       0 1084.86    78.1 1063.53   117.2 1047.71   136.7 1042.92   156.2 1031.06
   185.5 1018.37   234.3 1005.14   312.5  958.91     332  950.99   341.7   947.6
     371  943.09   410.1  941.21   468.5   943.7   512.8  942.91   527.8  942.39
   555.4  942.33   565.1  946.43   574.7  953.53   584.4   963.8   613.4  985.27
   632.7  995.42     681 1025.56   719.6 1045.36   758.2 1060.16   777.6 1069.89
   854.8 1097.66   874.1 1108.44   883.8 1110.81   903.1 1120.75   941.8 1129.89
#Mann= 3 , 0 , 0
       0      .1       0   512.8    .045       0   527.8      .1       0
Bank Sta=512.8,527.8
XS Rating Curve= 0 ,0
Exp/Cntr=0.3,0.1

Type RM Length L Ch R = 1 ,754.9   ,211.246,209.423,210.722
XS GIS Cut Line= 3
     1754891.804      370700.311     1754420.266      370669.676
     1753968.254      370700.265
#Sta/Elev= 30
       0 1061.78    77.1  1032.9   125.4 1011.95     135 1009.75   154.3  999.85
   173.6  992.17   183.2  986.01   192.9  982.25   202.5  972.17   212.2  960.12
   221.8  950.79   241.1   943.5   308.6  936.15     434   934.8     465  935.63
     480  936.33   491.8   936.9   501.5  939.86   520.7  956.25   588.2  994.27
   597.8   996.2   636.4 1012.68     646  1015.2     675 1028.63   684.6 1030.38
   732.8 1045.84   742.4 1047.48   829.2 1073.09   877.4 1090.65   925.6 1106.16
#Mann= 3 , 0 , 0
       0      .1       0     465    .045       0     480      .1       0
Bank Sta=465,480
XS Rating Curve= 0 ,0
Exp/Cntr=0.3,0.1

Type RM Length L Ch R = 1 ,545.5   ,351.681,353.543,355.406
XS GIS Cut Line= 3
     1754992.197      370377.038     1754558.182      370475.373
     1753947.736      370476.939
#Sta/Elev= 30
       0 1018.93    48.4 1002.32   116.1   996.3   154.8  987.15   183.8  978.63
   212.8  966.93   251.5  958.63   280.6  948.55   290.2  943.23   299.9  940.75
   319.3  938.81     387  937.24   512.8  936.95   581.5  933.25   596.5  932.67
   609.7  932.08   619.4  932.49   629.1  937.73   638.8  948.12   648.5  952.31
   658.2  962.04   677.6  974.24   687.3  982.14   696.9  986.57   735.7   993.7
   784.2  1009.3   822.9 1018.72   929.5 1049.18   968.3 1057.72  1055.5 1070.32
#Mann= 3 , 0 , 0
       0      .1       0   581.5    .045       0   596.5      .1       0
Bank Sta=581.5,596.5
XS Rating Curve= 0 ,0
Exp/Cntr=0.3,0.1

Type RM Length L Ch R = 1 ,191.9   ,204.282,191.912,179.541
XS GIS Cut Line= 3
     1754942.656       370041.45     1754415.706      370141.504
     1754022.162      370114.822
#Sta/Elev= 30
       0  938.97    19.5  938.92    87.8  936.48   224.3  933.36   263.3  932.94
   312.1  933.65   390.1  933.11   458.3  933.19   507.1   932.6   565.2  930.82
   594.1  929.34   603.7  927.76     612  925.99   613.3  925.71     623  925.22
     627     926   632.6  927.09   642.2  931.13   651.8  934.25   661.4  935.82
   671.1  936.65   728.8  937.36   767.3  938.44   796.1  938.43   844.2  937.56
   853.8  938.31   863.5  940.53   882.7  944.07   921.2  944.89   930.8  944.86
#Mann= 3 , 0 , 0
       0      .1       0     612    .045       0     627      .1       0
Bank Sta=612,627
XS Rating Curve= 0 ,0
Exp/Cntr=0.3,0.1

Chan Stop Cuts=-1
Use User Specified Reach Order=0